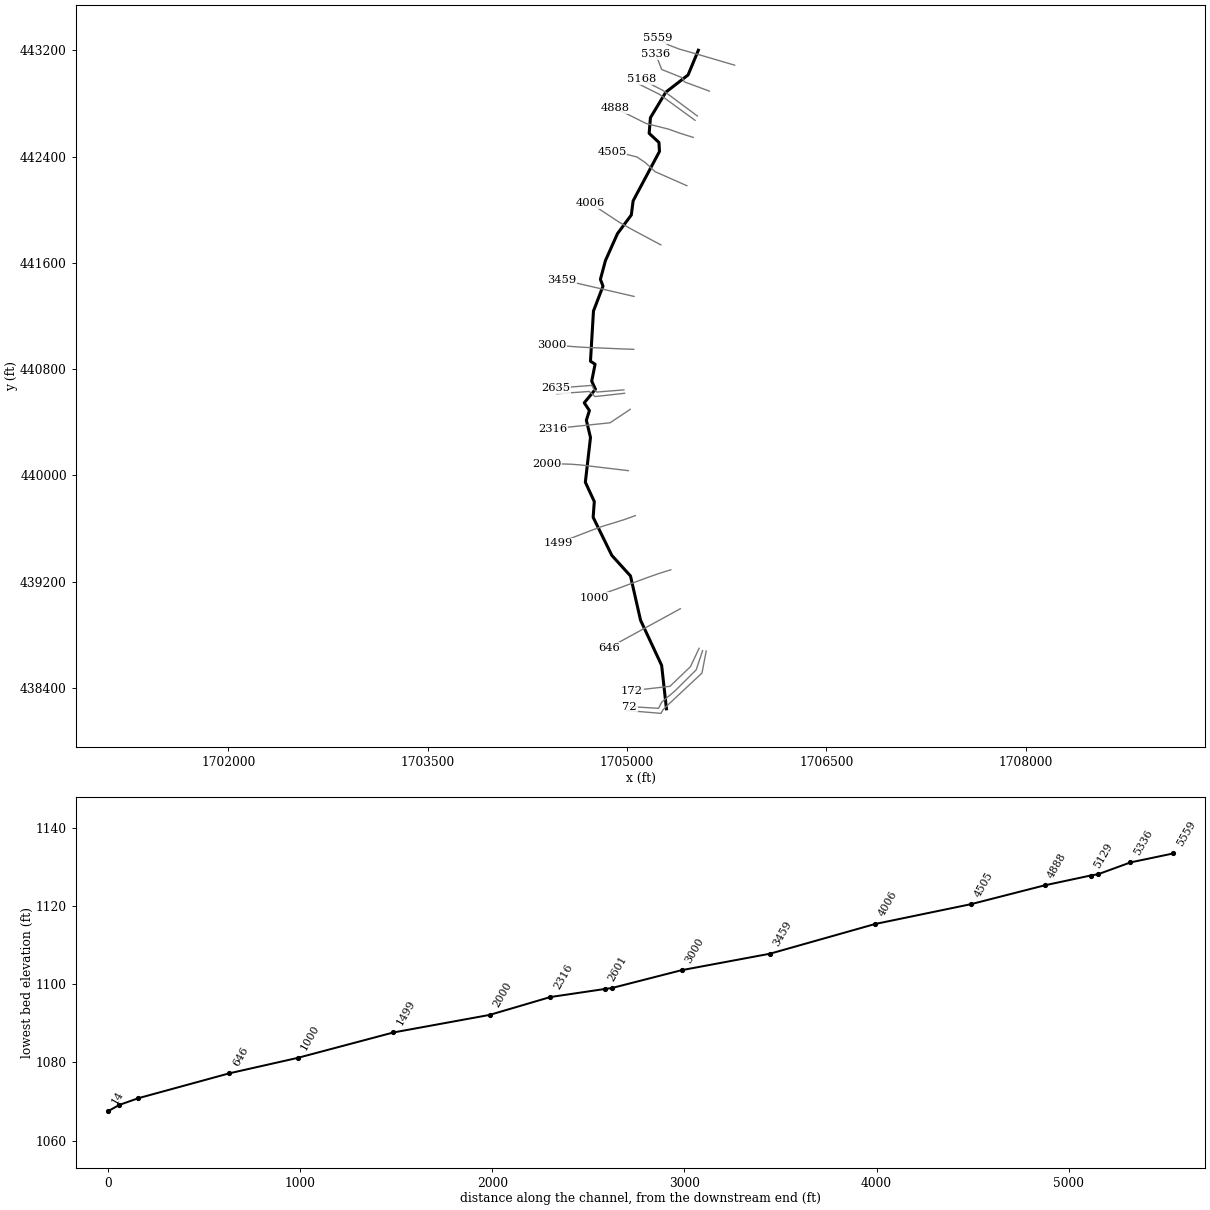
--- CAPPORNT1.prj (project) ---

Proj Title=CAPPORNT1
Current Plan=p01
Default Exp/Contr=0,0
English Units
Geom File=g01
Flow File=f01
Plan File=p01
BEGIN DESCRIPTION:
---------- MODELED AS PART OF WVEMD CTP PROGRAM, 2023----------
Stream Name: Cappo Run Tributary 1
Flood Zone:  AFH
Wetzel County, WV
HEC-RAS Version: RAS 6.3
Vertical Datum: NAVD88
Projection: NAD 1983 StatePlane West Virginia S FIPS 4702 (US Feet)
Terrain: 1-meter West Virginia FEMA R3 South Central (collected 2018-2020)
Land Use: 2019 NLCD
Hydrologic Method:
WV SIR2010-5033 regression equations
Additional Model Notes:
None
END DESCRIPTION:
DSS Export Rating Curves= 0
DSS Export Rating Curve Sorted= 0
DSS Export Volume Flow Curves= 0
DXF OffsetX= 0
DXF OffsetY= 0
DXF ScaleX= 0
DXF ScaleY= 0

--- CAPPORNT1.p01 (plan) ---

Plan Title=Floodplain
Program Version=6.31
Short Identifier=Floodplain
Geom File=g01
Flow File=f01
Subcritical Flow
K Sum by GR= 0
Std Step Tol= 0.01
Critical Tol= 0.01
Num of Std Step Trials= 20
Max Error Tol= 0.3
Flow Tol Ratio= 0.001
Split Flow NTrial= 30
Split Flow Tol= 0.02
Split Flow Ratio= 0.02
Log Output Level= 0
Friction Slope Method= 1
Unsteady Friction Slope Method= 2
Unsteady Bridges Friction Slope Method= 1
Parabolic Critical Depth
Global Vel Dist= 0 , 0 , 0
Global Log Level= 0
CheckData=True
Encroach Param=-1 ,0,0, 0
Mapping Interval=1HOUR
Computation Time Step Use Courant=        0
Computation Time Step Use Time Series=    0
Computation Time Step Count To Double=0
Computation Time Step Max Doubling=0
Computation Time Step Max Halving=0
Computation Time Step Residence Courant=0
Run HTab= 0
Run UNet= 0
Run Sediment= 0
Run PostProcess= 0
Run WQNet= 0
Run RASMapper=-1
UNET Theta= 0
UNET Theta Warmup= 0
UNET ZTol= 0
UNET ZSATol= 0
UNET MxIter= 0
UNET Max Iter WO Improvement= 0
UNET MaxInSteps= 0
UNET DtIC= 0
UNET DtMin= 0
UNET MaxCRTS= 0
UNET WFStab= 0
UNET SFStab= 0
UNET WFX= 1
UNET SFX= 1
UNET Gravity=32.17405
UNET 1D Methodology=Finite Difference
UNET DSS MLevel= 1
UNET Pardiso=0
UNET DZMax Abort= 0
UNET Use Existing IB Tables= 0
UNET Froude Reduction=False
UNET Froude Limit= 0
UNET Froude Power= 0
UNET D1 Cores= 0
UNET WindReference=Eulerian
UNET WindDragFormulation=Hsu (1988)
UNET D2 Coriolis=0
UNET D2 Cores= 0
UNET D2 Theta= 1
UNET D2 Theta Warmup= 1
UNET D2 Z Tol= 0.01
UNET D2 Volume Tol= 0.01
UNET D2 Max Iterations= 20
UNET D2 Equation= 0
UNET D2 RampUpFraction=0.1
UNET D2 TimeSlices= 1
UNET D2 Turbulence Formulation=Non-Conservative (original)
UNET D2 Eddy Viscosity=0.3
UNET D2 Transverse Eddy Viscosity=0.1
UNET D2 Smagorinsky Mixing=0
UNET D2 BCVolumeCheck=0
UNET D2 Cores=0
UNET D2 SolverType=PARDISO (Direct)
UNET D2 Minimum Iterations= 3
UNET D2 Maximum Iterations= 30
UNET D2 Restart Number= 10
UNET D2 Relaxation Coeff=1.3
UNET D2 SOR Precondition Iterations= 10
UNET D2 ILUT Maximum Fill= 8
UNET D2 ILUT Tolerance=1E-08
UNET D2 Convergence Tolerance=0.00001
UNET D1D2 MaxIter= 0
UNET D1D2 ZTol=0.01
UNET D1D2 QTol=0.1
UNET D1D2 MinQTol=1
Write IC File= 0
Write IC File at Fixed DateTime=0
Write IC File at Sim End=0
Echo Input=False
Echo Parameters=False
Echo Output=False
Write Detailed= 0
HDF Write Warmup=0
HDF Write Time Slices=0
HDF Flush=0
HDF Compression= 1
HDF Chunk Size= 1
HDF Spatial Parts= 1
HDF Use Max Rows=0
HDF Fixed Rows= 1
Calibration Method= 0
Calibration Iterations= 20
Calibration Max Change=0.05
Calibration Tolerance=0.2
Calibration Maximum=1.5
Calibration Minimum=0.5
Calibration Optimization Method= 1
WQ AD Non Conservative
WQ ULTIMATE=-1
WQ Max Comp Step=1HOUR
WQ Output Interval=15MIN
WQ Output Selected Increments= 0
WQ Create Restart=0
WQ Fixed Restart=0
WQ System Summary=0
WQ Write To DSS=0
Sorting and Armoring Iterations= 10
XS Update Threshold= 0.02
Bed Roughness Predictor= 0
Hydraulics Update Threshold= 0.02
Energy Slope Method= 1
Volume Change Method= 1
Sediment Retention Method= 0
Sediment TS Multiplier= 1
Warm Up Method= 0
XS Weighting Method= 0
Number of US Weighted Cross Sections= 1
Number of DS Weighted Cross Sections= 1
Upstream XS Weight=0
Main XS Weight=1
Downstream XS Weight=0
Number of DS XS's Weighted with US Boundary= 1
Upstream Boundary Weight= 1
Weight of XSs Associated with US Boundary= 0
Number of US XS's Weighted with DS Boundary= 1
Downstream Boundary Weight= 0.5
Weight of XSs Associated with DS Boundary= 0.5
Percentile Method= 0
Sediment Output Level= 3
Mass or Volume Output= 0
Output Increment Type= 1
Profile and TS Output Increment= 1
Transport Output Increment 1
XS Output Flag= 0
XS Output Increment= 10
Read HDF5 Sediment Hotstart= 0
Sediment Hotstart Type= 0
Write Gradation File= 0
Read Gradation Hotstart= 0
Write HDF5 File= 1
Write Binary Output= 1
Write DSS Sediment File= 0
DSS Sediment Output Type= 1
SV Curve= 0
Specific Gage Flag= 0
Subcell Erosion Methods= 0
Subcell Deposition Methods= 0
Advection Scheme= 1
Matrix Solver= 0
Implicit Weighting Factor= 1
Maximum Outer Loop Convergence Iterations= 5
Convergence Maximum Absolute= 0.001
Convergence RMSE= 0.0001
Grain Fractions Max Abs Error= 0.001
Max Subgrid Regions= 1
Max Subgrid Length Scale= 3.402823E+38
Initial Layer Thickness= 3.402823E+38
Min Layer Thickness= 3.402823E+38
Max Layer Thickness= 3.402823E+38
Number of Layers= 5

--- CAPPORNT1.f01 (steady flow) ---

Flow Title=Flow
Program Version=6.31
Number of Profiles= 1
Profile Names=F01pct
River Rch & RM=CAPPORNT1,Main            ,5559
     654
River Rch & RM=CAPPORNT1,Main            ,3000
     746
Boundary for River Rch & Prof#=CAPPORNT1,Main            , 1
Up Type= 0
Dn Type= 3
Dn Slope=0.0155
DSS Import GetInterval= 0
DSS Import GetPeak= 0
DSS Import FillOption= 0

--- CAPPORNT1.g01 (geometry) ---

Geom Title=Geometry
Program Version=6.31

River Reach=CAPPORNT1       ,Main
Reach XY= 30
     1705537.027      443200.671     1705459.667      443014.544
     1705291.723      442884.618     1705176.344      442692.871
     1705166.757      442575.178      1705240.48      442506.414
     1705244.447      442438.971     1705046.088      442067.048
     1705032.533      441960.926     1704928.395      441820.421
     1704837.811      441617.764     1704799.792      441476.268
1704819.34122261441425.254771373     1704747.557      441237.576
     1704725.077      440860.032     1704759.789      440837.221
     1704734.334       440709.94     1704762.434       440649.11
     1704678.132      440546.955     1704717.142      440488.439
     1704694.124      440415.893     1704725.118       440285.72
     1704686.397      439949.233     1704753.839      439803.769
     1704745.243      439685.084     1704885.748      439398.455
     1705026.252      439243.735     1705101.959      438910.491
     1705260.646      438570.636      1705296.95      438243.756

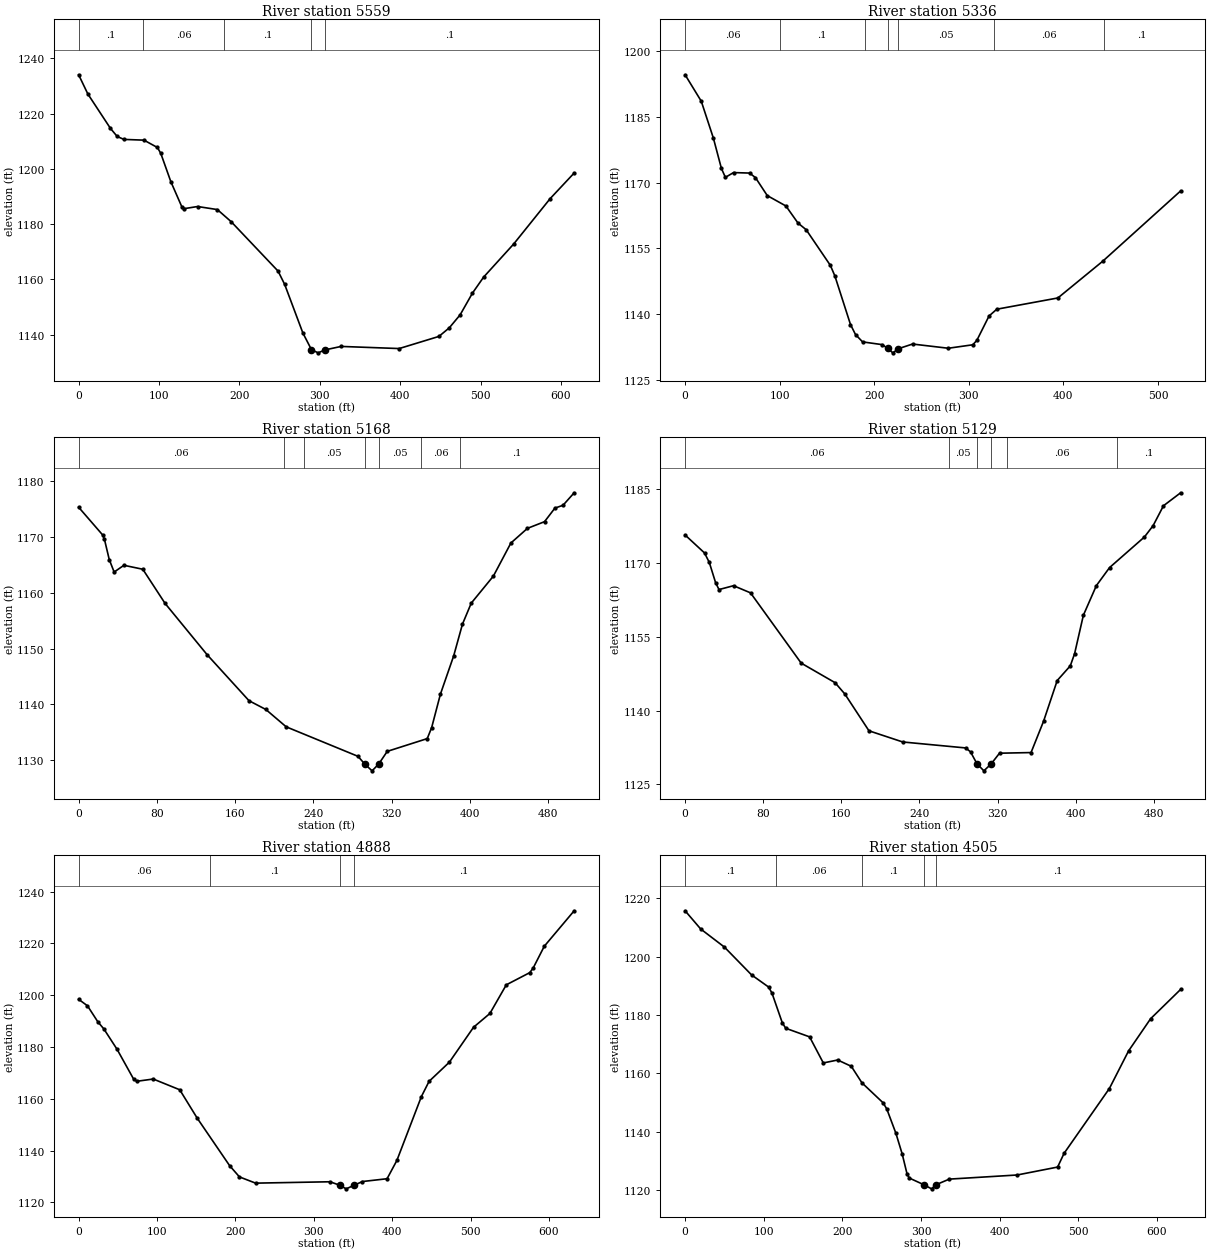
Type RM Length L Ch R = 1 ,5559    ,226,223.6,216
XS GIS Cut Line= 6
1705810.14630405443088.3059012351705564.35348855443160.516714817
1705468.22179104443188.1357540541705395.97226363443208.509400984
1705313.54362271443240.0008078121705230.55724013443290.258581316
#Sta/Elev= 30
       0 1234.05    11.5 1227.08    39.6 1214.64      48 1211.72    56.3 1210.66
    81.3 1210.39      98 1207.73   102.2 1205.61   114.7 1195.37   128.5 1186.19
   131.4  1185.6     148 1186.37   172.6 1185.26   189.7  1180.9   248.1    1163
   256.3  1158.2     279 1140.58   289.7 1134.54     298 1133.41   306.4 1134.47
   326.6 1135.73   398.8 1134.96   448.2 1139.35   461.1 1142.45   474.6 1147.15
     490 1155.05   503.9 1160.84   541.3 1172.82   586.6 1189.22   616.5  1198.5
#Mann= 5 ,-1,0
       0      .1       0      80     .06       0   181.2      .1       0
   289.7    .045       0   306.4      .1       0
Bank Sta=289.7,306.4
XS Rating Curve= 0 ,0
Exp/Cntr(USF)=0,0
Exp/Cntr=0.3,0.1

Type RM Length L Ch R = 1 ,5336    ,165.9,167.9,171.3
BEGIN DESCRIPTION:
Structure 3 XS 4
END DESCRIPTION:
XS GIS Cut Line= 5
1705620.10542686442892.9002159751705431.83236125442962.679743789
1705414.71662801442994.2780205351705260.67502888443056.157979162
1705217.22739835443169.385137502
#Sta/Elev= 30
       0 1194.65    17.1 1188.61    29.9 1180.18    38.4 1173.25    42.6 1171.21
    51.2  1172.3    68.2 1172.19    74.4 1171.15    86.9 1167.04   106.6 1164.67
   119.4 1160.76     128 1159.25   153.6  1151.1   158.4 1148.67   174.9 1137.58
   180.2 1135.29   187.7 1133.61   208.6 1132.98  214.261132.109   219.7 1131.11
   225.6 1132.06   240.5 1133.12   278.3 1132.16   304.2 1132.95   308.5 1133.96
   321.4 1139.53   329.6 1141.08   394.2 1143.65   441.7 1152.06     524 1168.11
#Mann= 7 ,-1,0
       0     .06       0     100      .1       0     190     .05       0
  214.26    .045       0   225.6     .05       0  326.72     .06       0
  442.73      .1       0
Bank Sta=214.26,225.6
XS Rating Curve= 0 ,0
Exp/Cntr(USF)=0,0
Exp/Cntr=0.3,0.1

Type RM Length L Ch R = 1 ,5168    ,39.2,39.2,39.3
BEGIN DESCRIPTION:
Structure 3 XS 3
END DESCRIPTION:
XS GIS Cut Line= 3
1705529.26038122442705.9437452281705272.52438265442896.850000568
1705106.63342974442982.428666755
#Sta/Elev= 30
       0 1175.36    24.5  1170.4    26.4  1169.6    31.3 1165.98    36.3 1163.74
    46.3 1164.95    65.6 1164.24    88.4 1158.11   131.3 1148.93   174.2 1140.67
   191.4  1139.1   212.2 1135.99   285.6  1130.7   292.6  1129.3     300  1128.1
  306.771129.318   315.5 1131.59   356.4 1133.88   360.9 1135.85   369.9 1141.87
   383.4  1148.7   392.4  1154.4   401.4 1158.17     424 1163.01   441.9 1168.94
   458.8 1171.57   476.3 1172.77   486.9  1175.2   495.2 1175.71   506.6 1177.95
#Mann= 7 ,-1,0
       0     .06       0     210      .1       0     230     .05       0
   292.6    .045       0  306.77     .05       0  349.94     .06       0
  389.94      .1       0
Bank Sta=292.6,306.77
XS Rating Curve= 0 ,0
Exp/Cntr(USF)=0,0
Exp/Cntr=0.3,0.1

Type RM Length L Ch R = 1 ,5129    ,236.8,240.2,242.4
BEGIN DESCRIPTION:
Structure 3 XS 2
END DESCRIPTION:
XS GIS Cut Line= 3
1705512.14464798442673.0288736181705243.55929564442869.201508415
1705086.88450677442946.880605416
#Sta/Elev= 30
       0 1175.65    19.9    1172    24.8 1170.07    31.2 1165.99    34.7 1164.57
    49.6 1165.35      67  1163.9   118.9 1149.63   153.6 1145.66   163.5 1143.39
   188.3 1135.89   222.9 1133.62   287.3 1132.41   292.3 1131.62  298.851129.218
     306 1127.76  313.531129.189     322 1131.34   354.3 1131.47   367.1 1137.82
   381.1  1146.1   394.5 1149.08   398.9 1151.55   407.9 1159.36   421.2 1165.37
   434.7 1169.03   470.4 1175.24   479.3 1177.54   489.9 1181.58   507.5 1184.22
#Mann= 6 ,-1,0
       0     .06       0     270     .05       0  298.85    .045       0
  313.53     .05       0     330     .06       0   442.6      .1       0
Bank Sta=298.85,313.53
XS Rating Curve= 0 ,0
Exp/Cntr(USF)=0,0
Exp/Cntr=0.3,0.1

Type RM Length L Ch R = 1 ,4888    ,385.3,383,379.4
BEGIN DESCRIPTION:
Structure 3 XS 1
END DESCRIPTION:
XS GIS Cut Line= 6
1705498.85139401442544.4924864651705396.69050909442576.795899558
1705313.37112193442606.6275327981705143.23661968442649.749165717
1704994.55515851442723.7454088061704909.13702225442765.150837797
#Sta/Elev= 30
       0 1198.41    11.3 1195.89    24.5 1189.72    32.2 1186.96      49 1179.12
      70 1167.69    74.2 1166.76    95.2 1167.63     129 1163.48   151.2 1152.56
   192.7 1134.16   205.2 1129.84   225.8 1127.44   320.7 1127.97   333.1 1126.64
   341.3 1125.24  351.821126.669     362 1128.06   393.5 1129.14     406 1136.19
   437.3 1160.87   447.1 1166.74     473 1174.14   503.8 1187.61   524.7 1192.94
   545.6 1203.99   575.6 1208.71     580 1210.54   594.1  1218.9   632.2 1232.58
#Mann= 4 ,-1,0
       0     .06       0  167.15      .1       0   333.1    .045       0
  351.82      .1       0
Bank Sta=333.1,351.82
XS Rating Curve= 0 ,0
Exp/Cntr(USF)=0,0
Exp/Cntr=0.3,0.1

Type RM Length L Ch R = 1 ,4505    ,494.7,498.9,498.5
XS GIS Cut Line= 6
 1705450.4514996442181.1139671651705211.24102001442286.786984175
1705138.03709817442355.0046955051705074.94339234442397.142078429
1704985.42323017 442419.986849011704886.39193217442433.958277762
#Sta/Elev= 30
       0 1215.67    19.8 1209.44      50 1203.23    84.5 1193.71   106.2 1189.54
   110.5 1187.44   123.5 1177.36   127.9 1175.43   158.3 1172.48   175.7 1163.55
     194 1164.56   211.3  1162.4   224.8 1156.75   251.7  1149.9   256.4  1147.8
     268 1139.46     276 1132.37   282.1 1125.62     285 1124.13   304.2 1121.76
   313.3 1120.43   318.9 1121.83   335.9 1123.76   422.1 1125.17   473.6 1127.89
   481.8 1132.59   539.4 1154.79   563.8 1167.67   591.8 1178.69     630 1188.74
#Mann= 5 ,-1,0
       0      .1       0   115.7     .06       0  225.24      .1       0
   304.2    .045       0   318.9      .1       0
Bank Sta=304.2,318.9
XS Rating Curve= 0 ,0
Exp/Cntr(USF)=0,0
Exp/Cntr=0.3,0.1

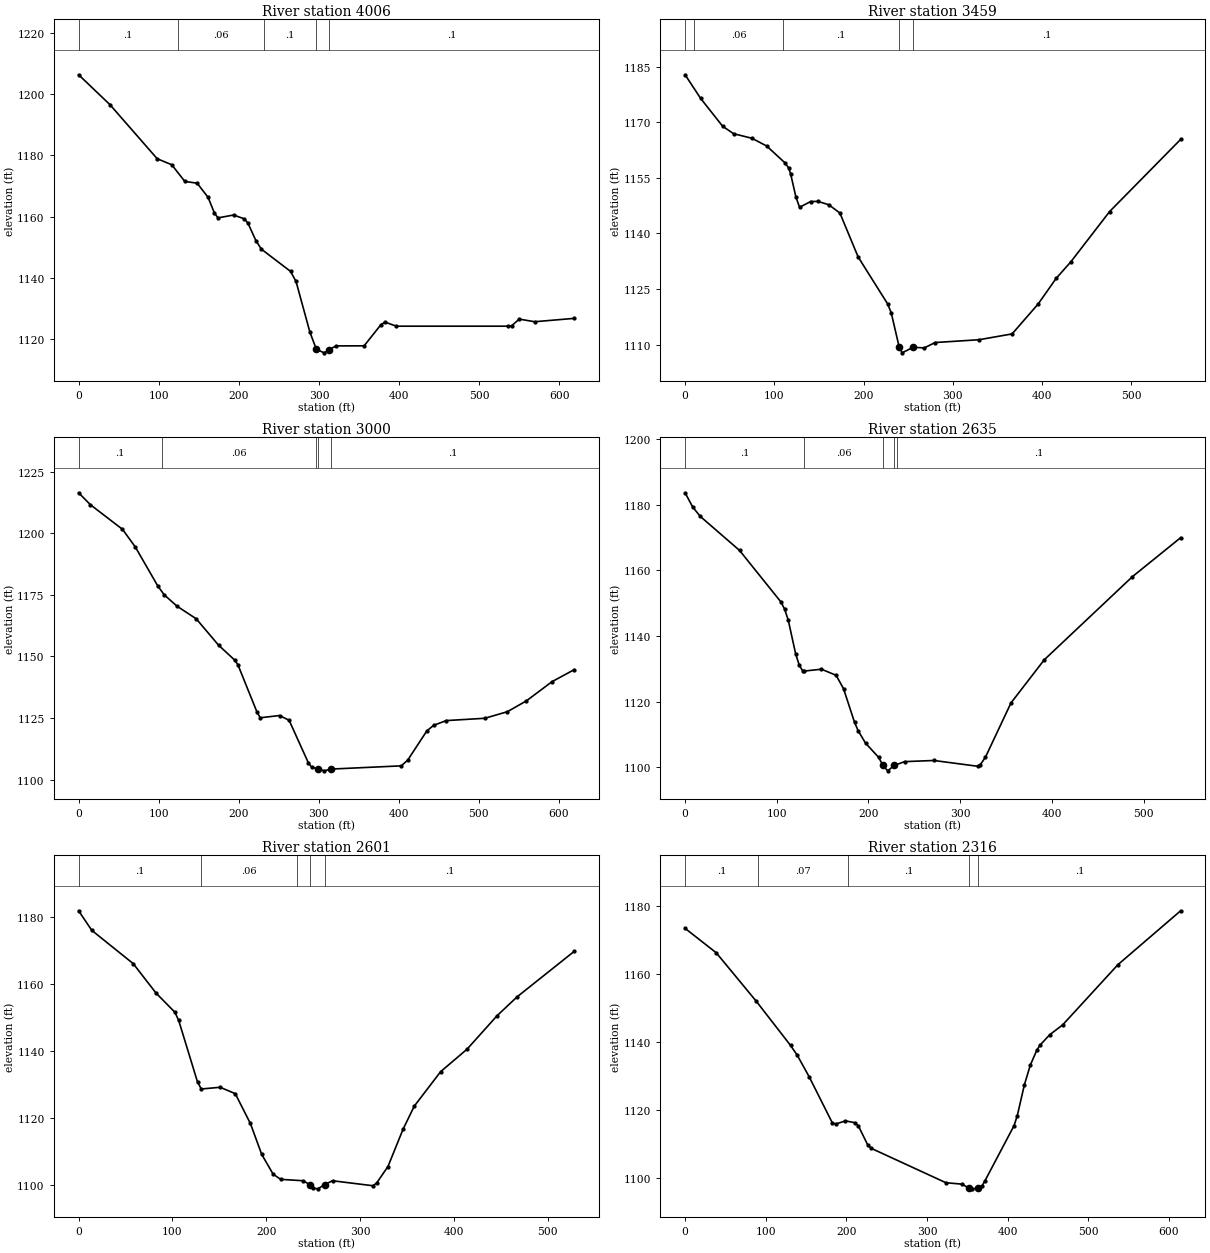
Type RM Length L Ch R = 1 ,4006    ,541.9,547.6,546.8
XS GIS Cut Line= 6
1705254.56540842441735.6893330961705028.69250059441856.421703175
1704941.39805576441906.1971941741704877.28827584441948.560954586
1704802.53973767441997.8174177561704723.01069726442050.493821591
#Sta/Elev= 30
       0 1206.44    39.1 1196.65      98 1178.95   116.2 1176.97   132.5 1171.51
   147.9 1170.93   161.5 1166.31   169.5 1161.13   173.9 1159.56   193.3 1160.51
   206.9 1159.24   211.4 1157.78   221.2 1152.14     228 1149.33   264.4 1142.05
   271.3 1138.74   288.6 1122.14   296.7  1116.5   306.5 1115.36   312.9 1116.44
   321.2 1117.63   356.3 1117.66   377.3  1124.6   382.3 1125.43   396.5 1124.09
   535.5 1124.09   540.3 1124.21   549.9 1126.41   569.1 1125.55   618.4 1126.65
#Mann= 5 ,-1,0
       0      .1       0   123.7     .06       0  231.15      .1       0
   296.7    .045       0   312.9      .1       0
Bank Sta=296.7,312.9
XS Rating Curve= 0 ,0
Exp/Cntr(USF)=0,0
Exp/Cntr=0.3,0.1

Type RM Length L Ch R = 1 ,3459    ,456.8,459,459.5
XS GIS Cut Line= 2
 1705053.1492076441347.6295489061704512.07287423441473.021882494
#Sta/Elev= 30
       0  1182.8    17.5  1176.4    42.1  1168.9    54.4 1166.89    74.9 1165.67
    91.4 1163.58   111.9 1159.04     116 1157.67   118.3 1156.04   124.2 1149.82
   128.3 1147.03   140.7  1148.6   148.9 1148.63   161.2 1147.71   173.5 1145.48
     194 1133.61   226.9 1121.01     231 1118.58  239.991109.272   243.3 1107.76
   255.6 1109.26     268 1109.09   280.3 1110.54   329.5  1111.3   366.5 1112.87
   395.7 1120.94   415.8 1127.83   432.2 1132.28   475.8 1145.89   555.4 1165.36
#Mann= 5 ,-1,0
       0      .1       0      10     .06       0     110      .1       0
  239.99    .045       0   255.6      .1       0
Bank Sta=239.99,255.6
XS Rating Curve= 0 ,0
Exp/Cntr(USF)=0,0
Exp/Cntr=0.3,0.1

Type RM Length L Ch R = 1 ,3000    ,364.6,364.3,356.2
BEGIN DESCRIPTION:
Structure 2 XS 4
END DESCRIPTION:
XS GIS Cut Line= 6
1705050.91719368 440949.590511591704957.19395593440952.741095841
1704794.88128842440959.8621445891704693.68004726440963.627885088
1704616.74909876440968.290277332 1704432.7232201440982.913935751
#Sta/Elev= 30
       0 1216.45    14.8 1211.58    54.8 1201.62    70.8 1194.46    98.9 1178.62
   106.9 1175.05   122.9 1170.41   146.9  1165.3   174.9 1154.56     195 1148.52
     199 1146.65     223 1127.31     227 1125.11     251 1126.02     263 1124.09
     287 1106.85     291 1105.11     299  1104.3     307 1103.56   315.1 1104.27
   403.2 1105.59   411.2 1107.91   435.2 1119.82   443.7 1122.04   459.3 1123.96
   507.5  1124.9   535.7 1127.56   559.6 1131.99   591.5 1139.76   619.2 1144.63
#Mann= 5 ,-1,0
       0      .1       0  103.78     .06       0  296.24      .1       0
     299    .045       0   315.1      .1       0
Bank Sta=299,315.1
XS Rating Curve= 0 ,0
Exp/Cntr(USF)=0,0
Exp/Cntr=0.3,0.1

Type RM Length L Ch R = 1 ,2635    ,33.7,34,34.3
BEGIN DESCRIPTION:
Structure 2 XS 3
END DESCRIPTION:
XS GIS Cut Line= 5
1704976.33122689 440644.27200639 1704771.7341455440627.836229768
1704752.46461429440645.4055082261704735.07025896440678.057824488
1704463.74505954440657.067049748
#Sta/Elev= 30
       0 1183.57     8.2 1179.28    16.3 1176.45    59.4 1166.03   104.6 1150.33
   108.6 1148.15   112.6 1144.72   120.6 1134.55   124.6 1131.05   128.6 1129.22
     130 1129.33   148.7  1129.9   164.7 1128.05   172.8 1123.97   184.8 1113.76
   188.8 1111.16   196.8 1107.42   211.1 1103.08  215.871100.605     221 1098.98
   228.1 1100.62   239.4 1101.78   271.3 1102.13   319.4 1100.36   322.1  1100.9
   327.5 1103.08   355.5 1119.66   391.7 1132.75   487.9 1158.05   540.5 1169.91
#Mann= 5 ,-1,0
       0      .1       0     130     .06       0  215.87    .045       0
   228.1     .06       0  231.33      .1       0
Bank Sta=215.87,228.1
XS Rating Curve= 0 ,0
Exp/Cntr(USF)=0,0
Exp/Cntr=0.3,0.1

Type RM Length L Ch R = 1 ,2601    ,280,285,289.4
BEGIN DESCRIPTION:
Structure 2 XS 2
END DESCRIPTION:
XS GIS Cut Line= 4
1704981.99873607440618.7682150811704760.39912714440593.831174689
 1704715.0590537440632.3702371121704470.22265713440614.800958655
#Sta/Elev= 30
       0 1181.94      14 1176.09    58.2 1166.12    82.4 1157.35   102.5 1151.61
   106.6 1149.15   126.7  1130.7   130.7 1128.63   150.8 1129.14   166.9 1127.23
     183 1118.32   195.1 1109.05   207.2 1103.17   215.2  1101.6   239.3 1101.18
   246.41099.986   249.6 1098.96   254.9 1098.76     262 1100.01   270.5 1101.18
   313.5 1099.69   317.5 1100.48   329.6 1105.44   345.6 1116.54   357.6 1123.49
   385.7 1133.81   413.8 1140.52     446 1150.59   467.3 1156.22     528 1169.79
#Mann= 5 ,-1,0
       0      .1       0     130     .06       0     233      .1       0
   246.4    .045       0     262      .1       0
Bank Sta=246.4,262
XS Rating Curve= 0 ,0
Exp/Cntr(USF)=0,0
Exp/Cntr=0.3,0.1

Type RM Length L Ch R = 1 ,2316    ,317.1,316.3,313.9
BEGIN DESCRIPTION:
Structure 2 XS 1
END DESCRIPTION:
XS GIS Cut Line= 3
1705024.24132178440497.5955984611704872.67644892 440396.62595575
1704442.68078822440351.784995547
#Sta/Elev= 30
       0 1173.49    38.6  1166.3    88.5 1151.93   130.7 1138.99     139 1136.11
     154 1129.65   182.6 1116.11   186.7 1115.79   198.8 1116.73   210.8 1116.18
   214.9 1115.22   226.4 1109.65   230.9 1108.62   323.4 1098.49   343.6 1098.07
   351.6  1096.9   355.6 1096.69   363.7 1096.89   367.7 1097.38   371.7 1099.02
   407.9 1115.34   411.9  1118.3   420.6 1127.31     428 1133.15     436 1137.54
   440.1 1139.08   452.1 1142.13   468.2 1145.05   536.6 1162.78   614.4 1178.68
#Mann= 5 ,-1,0
       0      .1       0      90     .07       0  202.12      .1       0
   351.6    .045       0   363.7      .1       0
Bank Sta=351.6,363.7
XS Rating Curve= 0 ,0
Exp/Cntr(USF)=0,0
Exp/Cntr=0.3,0.1

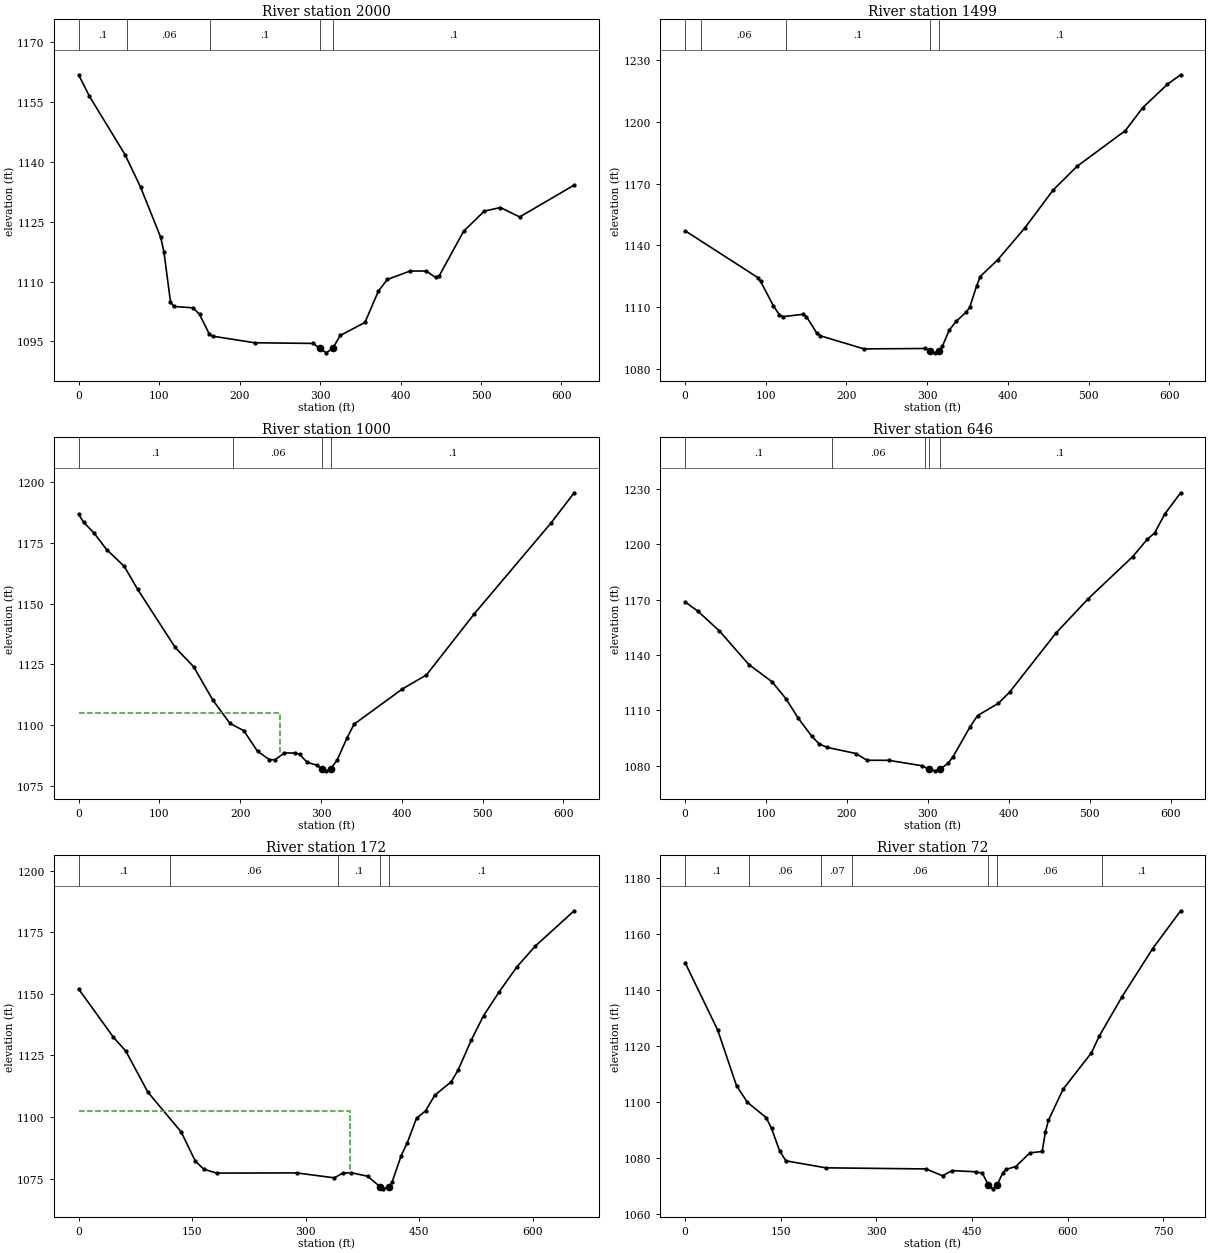
Type RM Length L Ch R = 1 ,2000    ,497.2,500.8,503.2
XS GIS Cut Line= 6
1705009.38381217440036.2357110081704916.30132118440047.404323846
1704655.67093693440078.6795237511704580.80330451440084.691650838
1704491.88419101440087.336658672  1704396.459185440088.879634589
#Sta/Elev= 30
       0 1161.87    13.4 1156.49    57.7 1141.82      77 1133.67     102 1121.09
     106 1117.43   114.1 1104.98   118.1 1103.75   142.3 1103.41   150.3 1101.75
   162.4 1096.82   166.5  1096.3   218.8 1094.65   291.3 1094.48     300 1093.21
   307.8 1092.12   315.81093.268   325.1 1096.48   355.8 1099.74   372.4 1107.55
   383.6 1110.53     412 1112.64     432 1112.64   443.5 1111.03   448.1 1111.43
   478.5 1122.65   504.1 1127.67   524.1 1128.57   548.1 1126.21   615.8  1134.2
#Mann= 5 ,-1,0
       0      .1       0      60     .06       0  163.75      .1       0
     300    .045       0   315.8      .1       0
Bank Sta=300,315.8
XS Rating Curve= 0 ,0
Exp/Cntr(USF)=0,0
Exp/Cntr=0.3,0.1

Type RM Length L Ch R = 1 ,1499    ,499.4,499.2,499.4
XS GIS Cut Line= 6
1705062.41356176 439697.824642421704973.30809693 439665.81355159
1704889.19277959 439639.762750671704817.15355359439618.115484253
1704723.32434492439583.4974432591704484.29496734439491.144609585
#Sta/Elev= 30
       0 1147.05    90.4 1124.19    93.5 1122.46   109.4 1110.54   116.9  1106.1
   121.1 1105.26   146.2 1106.36   150.4 1105.26   162.9 1097.45   167.3 1095.96
   221.7 1089.55   297.4 1089.75  303.99 1088.44   310.2 1087.63  314.85 1088.44
   318.8 1090.73   327.3 1098.62   335.8  1102.9   348.6 1107.51   352.9 1109.91
   361.4 1120.26   365.8 1124.77   387.5 1132.91   421.4 1148.58   456.2 1166.89
   485.8 1178.42   545.8 1195.82   567.2 1206.95   597.8 1218.34   614.2 1222.97
#Mann= 5 ,-1,0
       0      .1       0      20     .06       0  124.68      .1       0
  303.99    .045       0  314.85      .1       0
Bank Sta=303.99,314.85
XS Rating Curve= 0 ,0
Exp/Cntr(USF)=0,0
Exp/Cntr=0.3,0.1

Type RM Length L Ch R = 1 ,1000    ,352.7,354.3,355.2
XS GIS Cut Line= 6
1705329.92680626439290.1085943431705240.35316651439262.155238166
1705157.76704559439233.2031963321704923.37611017439146.248973921
1704840.97371592439116.8002139181704753.52441576439080.864590257
#Sta/Elev= 30
       0 1186.89     6.1 1183.59    18.7 1179.31    34.6 1172.36    56.4 1165.46
    73.1 1155.92   119.5    1132   142.4 1124.02   166.1 1110.31   187.4 1100.64
   204.4 1097.69   221.5 1089.16   236.1 1085.76   242.8 1085.66   254.7 1088.48
   268.4 1088.47   273.4 1087.93   282.7 1084.71   295.2 1083.36  301.19 1081.84
   306.8 1081.12   311.9 1081.85   320.1 1085.63   332.4 1094.84     341 1100.36
   400.7 1114.86   430.6 1120.67     490 1145.95   584.7 1183.28   613.4 1195.75
#Mann= 4 ,-1,0
       0      .1       0  191.35     .06       0  301.19    .045       0
   311.9      .1       0
#XS Ineff= 2 , 0
           249.6 1104.83
Permanent Ineff=
       F       F
Bank Sta=301.19,311.9
XS Rating Curve= 0 ,0
Exp/Cntr(USF)=0,0
Exp/Cntr=0.3,0.1

Type RM Length L Ch R = 1 ,646     ,475.5,473.8,470.5
XS GIS Cut Line= 6
1705401.33954525438996.9126059771705242.30278983438909.970850727
1705088.74994732438826.0277771421705022.94167999438790.051799229
1704946.16558682438748.0791141451704863.90525266438703.109059727
#Sta/Elev= 30
       0 1168.82    15.9 1163.77    42.5 1153.02    78.9 1134.84   107.3 1125.57
   124.5 1116.42   139.7 1105.84   156.4 1096.05   165.5 1091.87   175.1 1089.96
   211.1 1086.59   224.8 1082.93   251.7 1082.89   293.2 1079.92     301 1078.05
   309.3 1077.19  315.041078.089   325.1 1081.29   331.3 1084.92   352.4  1101.2
   361.5 1107.15   387.3 1113.84   401.1 1119.87     458 1151.72   498.3 1170.58
     553 1193.28   571.2 1202.75   580.4 1206.27   592.8 1216.45   612.5 1228.03
#Mann= 5 ,-1,0
       0      .1       0  181.25     .06       0  296.25      .1       0
     301    .045       0  315.04      .1       0
Bank Sta=301,315.04
XS Rating Curve= 0 ,0
Exp/Cntr(USF)=0,0
Exp/Cntr=0.3,0.1

Type RM Length L Ch R = 1 ,172     ,95.6,100.1,103.4
BEGIN DESCRIPTION:
Structure 1 XS 4
END DESCRIPTION:
XS GIS Cut Line= 4
1705542.67644076438699.1731410571705477.65941041438561.011951581
1705323.24396335438413.0982075541705037.16902985438380.589692384
#Sta/Elev= 30
       0 1151.97      46 1132.35    62.4 1126.71    91.3 1110.15   135.5 1093.89
   154.1 1082.08   165.4 1078.78   182.4 1077.22   287.8  1077.3   337.6  1075.3
   348.7 1077.19   359.8  1077.4   381.8 1075.93   397.9 1071.69   401.9 1070.83
   410.3 1071.74     414 1073.62     426 1084.36   434.1 1089.58   446.2 1099.52
   458.2  1102.5   470.3 1108.84   492.1 1114.32   501.2  1119.1   518.6 1131.26
   534.7 1141.11   554.9 1150.58     579 1161.03   603.2 1169.42   654.4 1183.71
#Mann= 5 ,-1,0
       0      .1       0     120     .06       0  342.69      .1       0
   397.9    .045       0   410.3      .1       0
#XS Ineff= 2 , 0
           358.3 1102.48
Permanent Ineff=
       F       F
Bank Sta=397.9,410.3
XS Rating Curve= 0 ,0
Exp/Cntr(USF)=0,0
Exp/Cntr=0.3,0.1

Type RM Length L Ch R = 1 ,72      ,57.7,58.1,58.4
BEGIN DESCRIPTION:
Structure 1 XS 3
END DESCRIPTION:
XS GIS Cut Line= 6
1705568.96091966 438681.064089821705520.37856916438536.501973708
1705362.78216389438380.0905038151705260.87772139438293.590221223
1705237.17901383438247.3777414831705020.33583966 438260.41203064
#Sta/Elev= 30
       0  1149.9    51.2  1125.8    80.7 1105.92    97.6 1100.06   127.2 1094.54
   135.6 1090.68   148.3 1082.66   158.1 1079.11   220.6  1076.6     378  1076.2
     404 1073.74   418.7 1075.61   455.9 1075.19   466.4 1074.66  475.69 1070.52
   482.4 1069.09  489.58 1070.52   498.5 1074.87   503.9 1076.06   518.7 1077.07
   540.9 1081.95   560.2 1082.44   565.2 1089.38   570.1 1093.65     593 1104.69
   637.3 1117.65   649.9 1123.73   685.4 1137.73   733.5 1154.94   777.4 1168.46
#Mann= 7 ,-1,0
       0      .1       0     100     .06       0  212.51     .07       0
  262.51     .06       0  475.69    .045       0  489.58     .06       0
  654.24      .1       0
Bank Sta=475.69,489.58
XS Rating Curve= 0 ,0
Exp/Cntr(USF)=0,0
Exp/Cntr=0.3,0.1

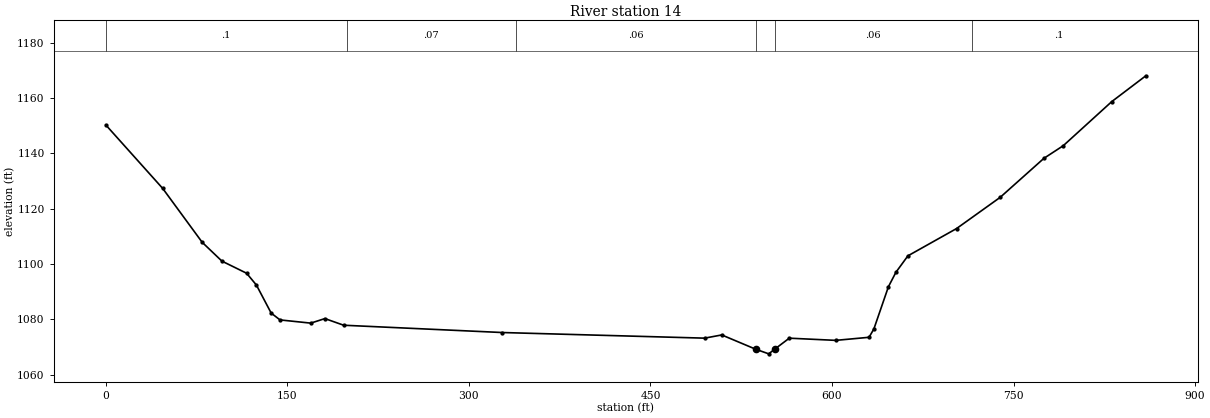
Type RM Length L Ch R = 1 ,14      ,,,
BEGIN DESCRIPTION:
Structure 1 XS 2
END DESCRIPTION:
XS GIS Cut Line= 6
1705596.21443335438678.6942190641705564.22117815438512.803266148
1705307.09020113 438272.261384421705271.03081781438236.240978775
1705255.45773233438209.3687770121705000.19193823438230.788646191
#Sta/Elev= 30
       0  1150.2      47 1127.26    79.6  1107.8    95.9    1101   116.3 1096.62
   124.4 1092.35   136.6 1082.22   143.9 1079.75   169.3 1078.59     181 1080.23
   196.5 1077.83   327.7 1075.19   494.7 1073.16   508.9 1074.32   537.1 1069.13
   547.7 1067.49  552.68 1069.19   564.7 1073.15   603.1 1072.36   630.6 1073.47
   634.6  1076.5   646.6 1091.74   652.8 1096.97   662.7 1102.91   702.9 1112.77
     739 1124.07   775.1 1138.16   791.1 1142.73   831.1 1158.64   859.3 1167.99
#Mann= 6 ,-1,0
       0      .1       0  198.95     .07       0  338.95     .06       0
   537.1    .045       0  552.68     .06       0   715.3      .1       0
Bank Sta=537.1,552.68
XS Rating Curve= 0 ,0
Exp/Cntr(USF)=0,0
Exp/Cntr=0.3,0.1
LCMann Table=0

Chan Stop Cuts=-1
Use User Specified Reach Order=0
Composite Channel Slope=5